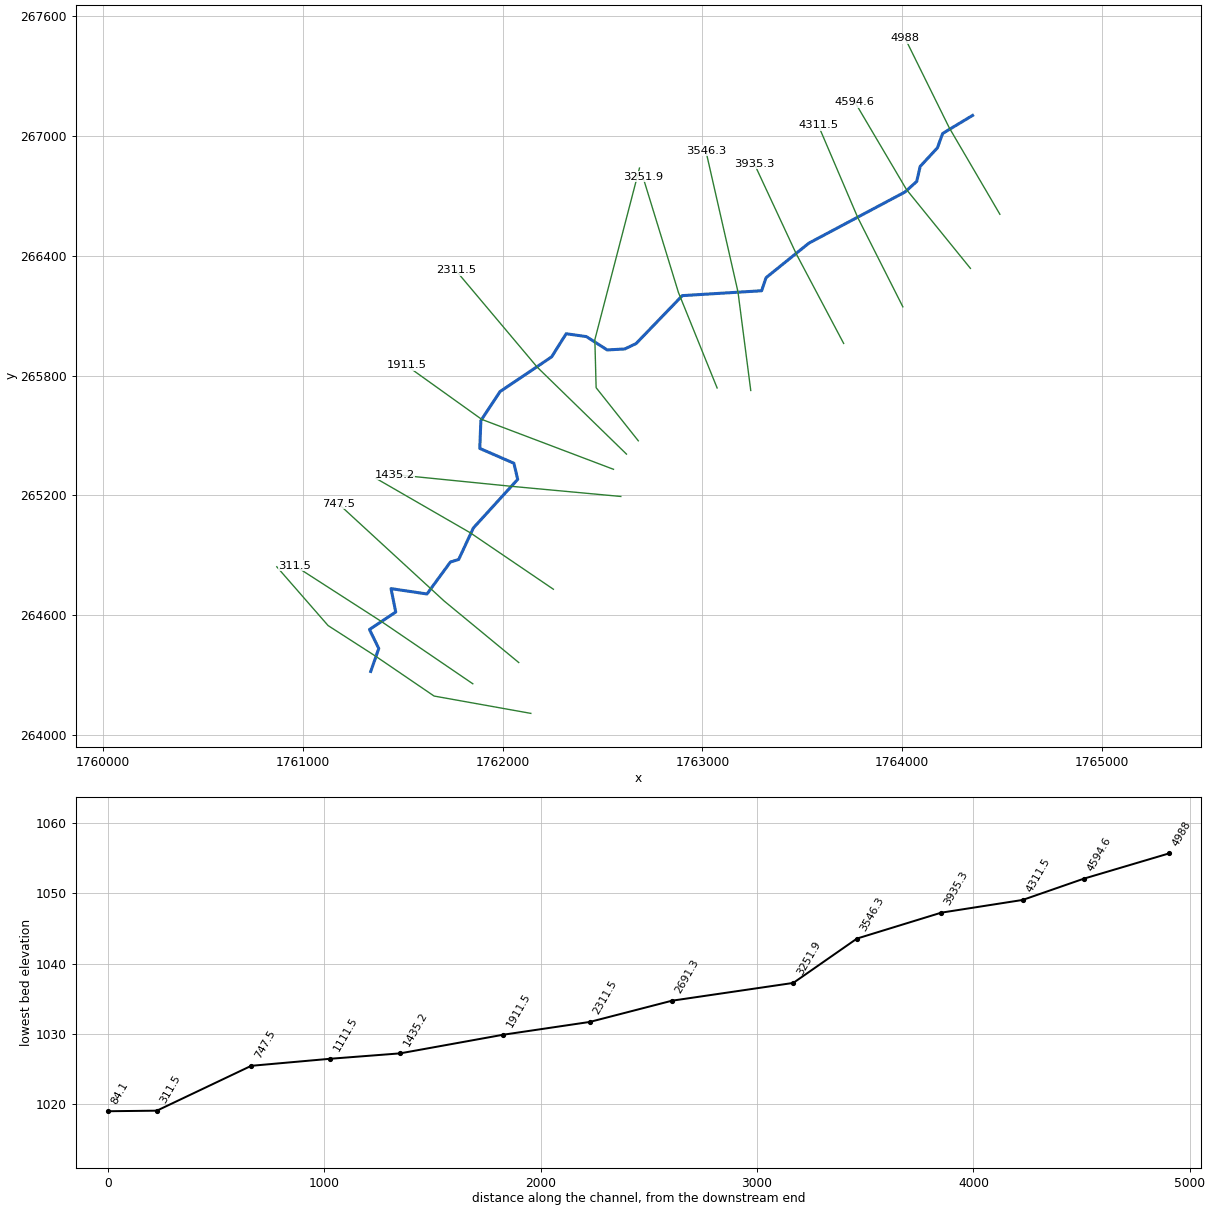
--- CoplnRnTr.prj (project) ---

Proj Title=CoplnRnTr
Current Plan=p01
Geom File=g01
Flow File=f01
Plan File=p01
DSS Export Rating Curves=0
DSS Export Rating Curve Sorted=0
DSS Export Volume Flow Curves=0
DXF OffsetX=0
DXF OffsetY=0
DXF ScaleX=0
DXF ScaleY=0

--- CoplnRnTr.p01 (plan) ---

Plan Title=Floodplain
Program Version=4.00
Geom File=g01
Flow File=f01
K Sum by GR=0
Std Step Tol=0.01
Critical Tol=0.01
Num of Std Step Trials=20
Max Error Tol=0.3
Flow Tol Ratio=0.001
Split Flow NTrial=30
Split Flow Tol=0.02
Split Flow Ratio=0.02
Log Output Level=0
Friction Slope Method=1
Unsteady Friction Slope Method=2
Unsteady Bridges Friction Slope Method=1
Global Log Level=0
CheckData=False
Run HTab=0
Run UNet=0
Run PostProcess=0
UNET Theta=0
UNET Theta Warmup=0
UNET ZTol=0
UNET ZSATol=0
UNET MxIter=0
UNET MaxInSteps=0
UNET DtIC=0
UNET DtMin=0
UNET MaxCRTS=0
UNET WFStab=0
UNET SFStab=0
UNET WFX=0
UNET SFX=0
UNET DSS MLevel=0
UNET DZMax Abort=0
UNET Convert EG Bridges=0
UNET Use Existing IB Tables=0
UNET Froude Limit=0
UNET Froude Power=0
Write IC File=0
Echo Input=False
Echo Output=False
Write Detailed=0

--- CoplnRnTr.f01 (steady flow) ---

Flow Title=NFF Regression Equation
Program Version=4.00
Number of Profiles=1
Profile Names=P100yr
River Rch & RM=CoplnRnTr,Main      ,4988
     722
River Rch & RM=CoplnRnTr,Main      ,2691.3
780.4385
River Rch & RM=CoplnRnTr,Main      ,2311.5
1112.304
River Rch & RM=CoplnRnTr,Main      ,311.5
1137.642
River Rch & RM=CoplnRnTr,Main      ,84.1
1137.642
Boundary for River Rch & Prof#=CoplnRnTr,Main      ,1
Up Type=0
Dn Type=3
Dn Slope=0.007164

--- CoplnRnTr.g01 (geometry) ---

Geom Title=USGS 3m DEM
Program Version=4.00

River Reach=CoplnRnTr     ,Main
Reach XY= 30
     1764352.513      267103.904     1764202.709      267013.371
     1764176.739      266941.620     1764090.246      266848.077
     1764072.982      266772.797     1764014.160      266719.897
     1763533.024      266463.451     1763318.870      266290.454
     1763296.740      266224.921     1762899.699      266200.429
     1762667.948      265959.797     1762611.394      265933.049
     1762523.658      265928.128     1762419.419      265995.090
     1762318.358      266009.458     1762245.621      265893.436
     1761986.984      265719.075     1761891.318      265573.541
     1761885.913      265434.469     1762056.626      265360.063
     1762075.680      265279.238     1761853.657      265035.369
     1761780.366      264877.790     1761738.863      264864.817
     1761621.714      264704.606     1761441.598      264731.525
     1761465.239      264614.048     1761333.792      264526.614
     1761380.293      264431.391     1761340.093      264316.280

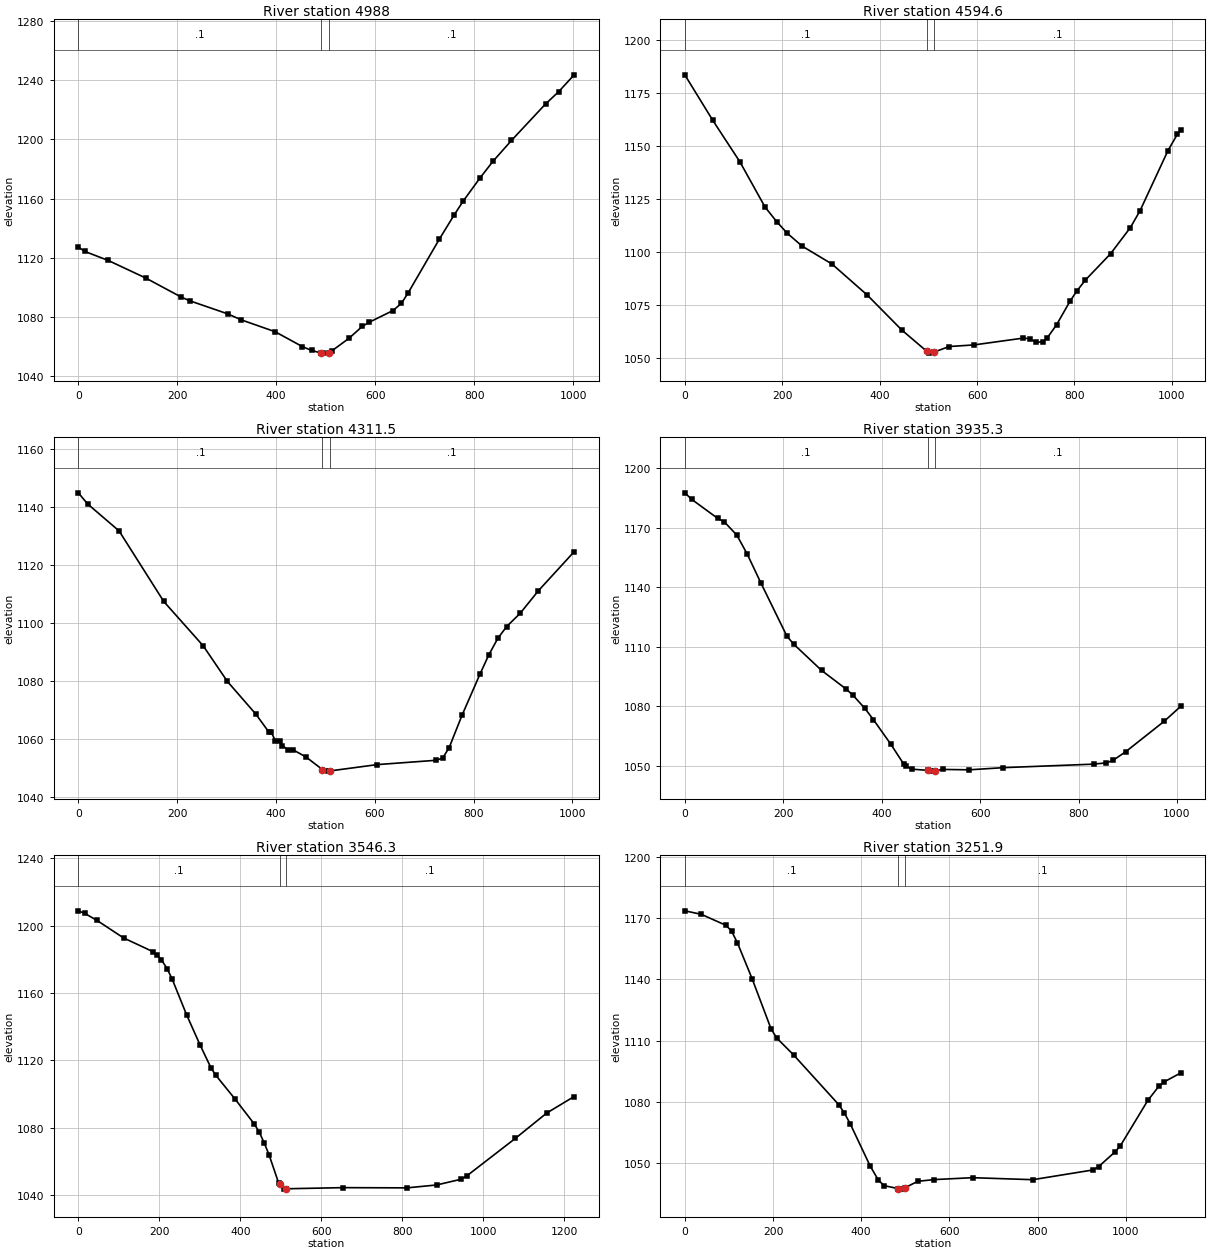
Type RM Length L Ch R = 1 ,4988,390.466,393.397,394.85
XS GIS Cut Line= 3
     1764489.288      266608.222     1764235.962      267041.666
     1764014.913      267490.403
#Sta/Elev= 30
       0 1127.25    12.8 1124.36    60.5 1118.22   136.6 1106.31   208.0 1093.51
   225.4 1090.99   301.6 1082.23   329.1 1078.18   397.9 1070.12   452.9 1060.10
   471.5 1057.48   490.9 1055.79   494.1 1055.69   505.9 1056.10   512.0 1057.10
   547.0 1065.66   573.8 1073.66   587.1 1076.38   636.2 1084.45   653.2 1089.33
   666.5 1096.22   729.6 1132.51   759.1 1148.61   778.0 1158.29   812.1 1173.95
   838.5 1185.25   875.6 1199.23   944.4 1223.80   970.9 1232.10  1002.3 1243.50
#Mann= 3 , 0 , 0
       0     0.1       0   490.9   0.045       0   505.9     0.1       0
Bank Sta=   490.9,   505.9
Exp/Cntr=0.3,0.1

Type RM Length L Ch R = 1 ,4594.6,287.908,283.11,279.69
XS GIS Cut Line= 3
     1764341.769      266337.041     1764021.707      266732.334
     1763763.198      267171.119
#Sta/Elev= 30
       0 1183.66    57.6 1162.08   113.0 1142.58   164.6 1121.21   189.0 1114.15
   210.4 1108.76   241.0 1102.67   302.1 1094.23   374.7 1079.52   445.5 1063.02
   497.2 1052.87   502.1 1052.10   512.2 1052.63   542.8 1055.22   594.1 1055.99
   694.4 1059.19   708.1 1058.92   721.9 1057.14   735.7 1057.59   743.9 1059.25
   763.3 1065.52   790.8 1076.63   804.6 1081.38   821.9 1086.53   874.0 1099.06
   914.8 1111.47   934.7 1119.48   991.7 1147.74  1011.3 1155.62  1017.9 1157.43
#Mann= 3 , 0 , 0
       0     0.1       0   497.2   0.045       0   512.2     0.1       0
Bank Sta=   497.2,   512.2
Exp/Cntr=0.3,0.1

Type RM Length L Ch R = 1 ,4311.5,375.766,376.267,374.613
XS GIS Cut Line= 3
     1764003.551      266144.347     1763777.753      266592.076
     1763580.632      267053.713
#Sta/Elev= 30
       0 1144.84    18.8 1141.01    82.4 1131.74   172.9 1107.45   252.7 1092.19
   301.7 1079.92   359.1 1068.71   385.7 1062.49   390.1 1062.57   398.8 1059.50
   407.7 1059.28   412.3 1057.85   425.1 1056.39   434.3 1056.43   460.8 1053.93
   493.9 1049.62   504.7 1049.07   508.9 1049.13   604.6 1051.31   724.7 1052.81
   737.6 1053.63   750.5 1057.19   776.3 1068.22   812.6 1082.38   830.7 1089.09
   848.8 1094.73   866.7 1098.81   894.1 1103.37   931.2 1111.18  1003.4 1124.58
#Mann= 3 , 0 , 0
       0     0.1       0   493.9   0.045       0   508.9     0.1       0
Bank Sta=   493.9,   508.9
Exp/Cntr=0.3,0.1

Type RM Length L Ch R = 1 ,3935.3,397.294,388.987,378.229
XS GIS Cut Line= 3
     1763707.233      265960.866     1763469.978      266409.862
     1763259.324      266862.820
#Sta/Elev= 30
       0 1187.50    14.3 1184.16    67.0 1174.60    80.5 1172.83   105.9 1166.12
   127.0 1156.54   154.8 1141.98   207.5 1115.26   221.0 1111.31   277.8 1098.03
   328.4 1088.50   341.8 1085.47   365.7 1078.93   383.3 1073.17   418.4 1060.88
   444.8 1050.82   449.3 1049.80   461.7 1048.25   493.3 1047.65   503.0 1047.26
   508.3 1047.51   524.1 1048.12   577.7 1047.92   647.1 1049.01   830.5 1050.78
   856.6 1051.43   869.7 1052.63   895.9 1057.05   974.5 1072.48  1007.4 1079.87
#Mann= 3 , 0 , 0
       0     0.1       0   493.3   0.045       0   508.3     0.1       0
Bank Sta=   493.3,   508.3
Exp/Cntr=0.3,0.1

Type RM Length L Ch R = 1 ,3546.3,289.136,294.373,298.005
XS GIS Cut Line= 3
     1763242.244      265724.906     1763178.197      266219.901
     1763017.390      266926.833
#Sta/Elev= 30
       0 1208.73    15.9 1207.19    45.8 1203.08   111.7 1192.64   183.5 1184.58
   194.3 1182.61   204.9 1179.79   219.5 1174.28   231.4 1168.36   267.3 1147.03
   300.3 1129.24   327.2 1115.70   339.2 1111.20   387.1 1096.98   434.9 1082.07
   446.9 1077.30   458.9 1070.97   470.9 1063.91   494.8 1047.01   497.4 1046.35
   506.9 1043.58   512.3 1043.79   653.0 1044.46   811.3 1044.33   884.4 1046.04
   945.2 1049.46   959.9 1051.59  1079.2 1073.74  1156.3 1088.72  1224.1 1098.54
#Mann= 3 , 0 , 0
       0     0.1       0   497.4   0.045       0   512.3     0.1       0
Bank Sta=   497.4,   512.3
Exp/Cntr=0.3,0.1

Type RM Length L Ch R = 1 ,3251.9,568.345,560.58,548.693
XS GIS Cut Line= 3
     1763073.875      265737.529     1762880.324      266216.139
     1762702.022      266797.242
#Sta/Elev= 30
       0 1173.50    37.3 1171.80    93.1 1166.43   105.9 1163.65   119.4 1157.78
   152.7 1140.22   195.5 1115.76   208.3 1111.27   246.8 1102.93   349.2 1078.58
   362.0 1074.44   375.2 1069.16   420.3 1048.56   438.9 1041.67   451.7 1038.99
   483.3 1037.54   490.1 1037.27   498.3 1037.85   528.1 1041.10   565.4 1041.94
   652.3 1042.87   788.9 1041.89   925.5 1046.66   938.0 1048.26   975.2 1055.45
   987.6 1058.52  1049.7 1080.68  1074.6 1087.58  1087.0 1089.80  1124.1 1094.12
#Mann= 3 , 0 , 0
       0     0.1       0   483.3   0.045       0   498.3     0.1       0
Bank Sta=   483.3,   498.3
Exp/Cntr=0.3,0.1

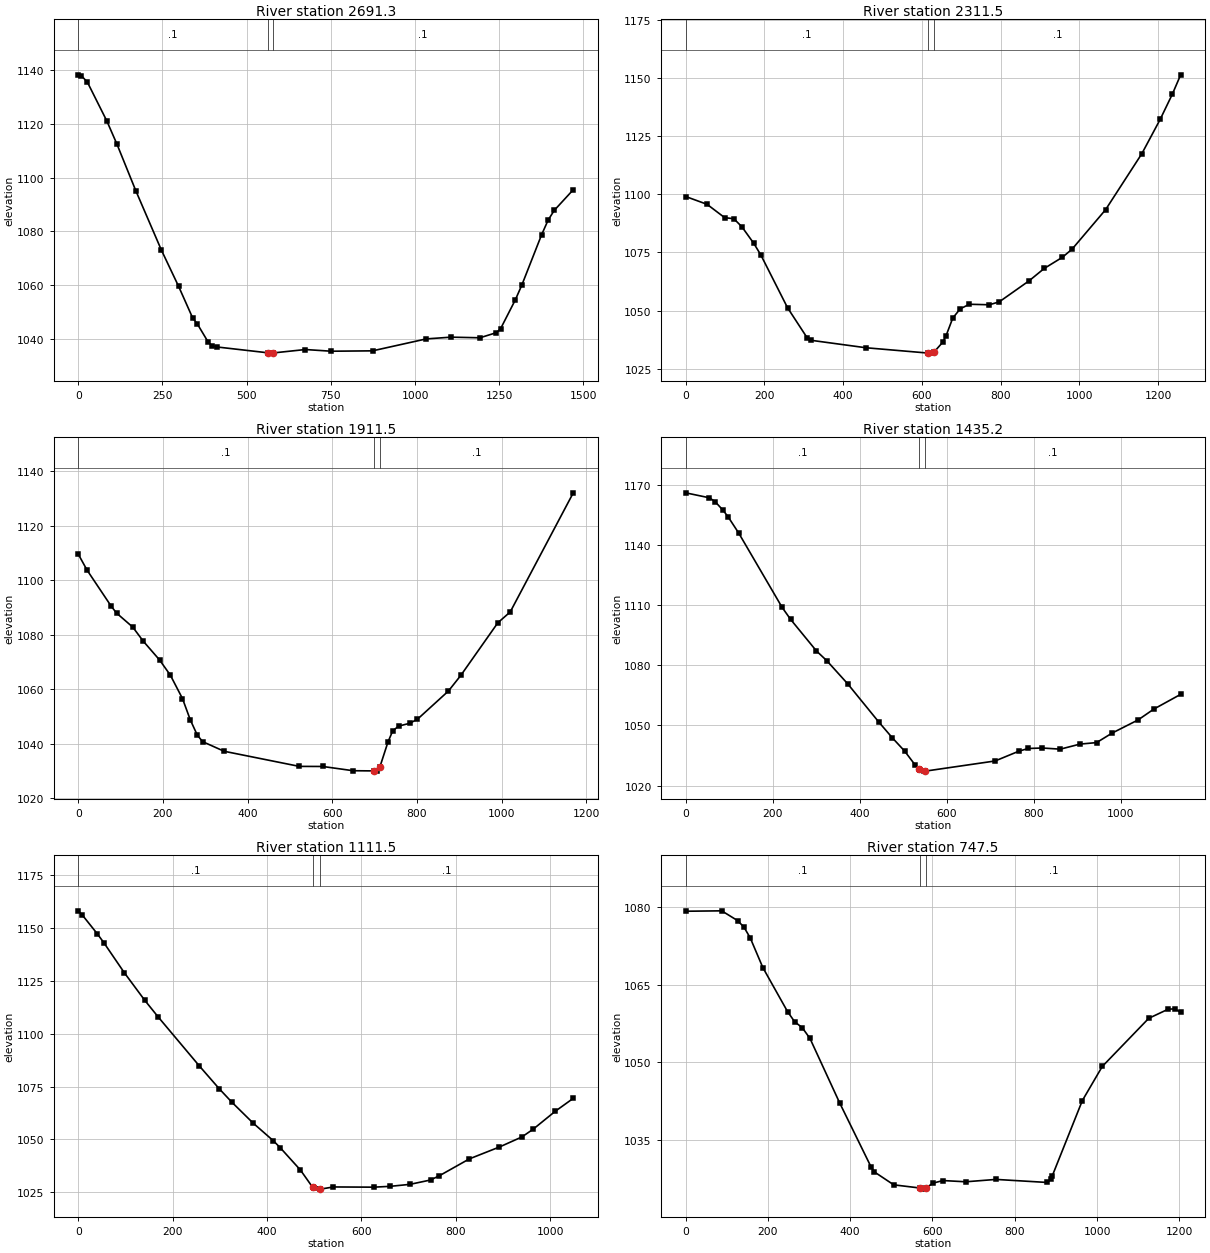
Type RM Length L Ch R = 1 ,2691.3,379.576,379.794,400.892
XS GIS Cut Line= 4
     1762679.419      265472.524     1762468.266      265738.784
     1762461.883      265979.710     1762685.254      266840.056
#Sta/Elev= 30
       0 1138.28     8.9 1137.97    26.9 1135.58    84.7 1121.12   115.0 1112.42
   170.6 1095.21   246.6 1073.11   298.0 1059.54   339.6 1047.82   353.6 1045.57
   385.8 1038.82   397.3 1037.46   413.0 1037.01     563 1034.86   567.4 1034.74
     578 1034.80   674.2 1036.08   750.9 1035.45   873.6 1035.59  1033.1 1040.03
  1106.7 1040.68  1192.5 1040.45  1241.6 1042.36  1253.8 1043.81  1297.5 1054.53
  1316.9 1060.05  1375.4 1078.71  1395.0 1084.24  1413.3 1087.87  1469.7 1095.54
#Mann= 3 , 0 , 0
       0     0.1       0     563   0.045       0     578     0.1       0
Bank Sta=     563,     578
Exp/Cntr=0.3,0.1

Type RM Length L Ch R = 1 ,2311.5,391.024,400,404.992
XS GIS Cut Line= 3
     1762620.151      265405.972     1762173.714      265841.504
     1761765.972      266326.751
#Sta/Elev= 30
       0 1099.02    54.3 1095.67    99.1 1089.93   122.3 1089.48   142.7 1086.03
   173.3 1078.83   191.4 1073.76   258.8 1051.22   308.6 1038.31   317.4 1037.26
   457.9 1034.03   616.2 1031.74   623.7 1031.72   631.2 1032.23   653.3 1036.45
   661.7 1039.29   678.6 1046.82   697.6 1050.76   720.7 1052.72   771.4 1052.50
   796.6 1053.75   872.4 1062.79   910.8 1068.10   957.3 1072.93   981.9 1076.45
  1066.7 1093.34  1158.9 1117.44  1205.4 1132.15  1236.4 1143.02  1257.5 1151.31
#Mann= 3 , 0 , 0
       0     0.1       0   616.2   0.045       0   631.2     0.1       0
Bank Sta=   616.2,   631.2
Exp/Cntr=0.3,0.1

Type RM Length L Ch R = 1 ,1911.5,470.164,476.359,487.904
XS GIS Cut Line= 3
     1762555.154      265329.721     1761895.649      265580.035
     1761518.334      265850.415
#Sta/Elev= 30
       0 1109.59    20.6 1103.77    77.8 1090.48    90.5 1087.95   128.6 1082.82
   153.8 1077.59   192.1 1070.73   217.5 1065.16   246.2 1056.55   264.6 1048.75
   281.0 1043.19   293.7 1040.74   344.5 1037.20   522.4 1031.64   577.6 1031.61
   649.3 1030.05   697.9 1029.98   700.1 1029.90   705.4 1030.02   712.9 1031.57
   731.9 1040.68   743.1 1044.73   757.1 1046.44   783.0 1047.47   801.5 1048.98
   874.6 1059.33   903.8 1065.06   991.4 1084.41  1020.6 1088.38  1169.6 1132.14
#Mann= 3 , 0 , 0
       0     0.1       0   697.9   0.045       0   712.9     0.1       0
Bank Sta=   697.9,   712.9
Exp/Cntr=0.3,0.1

Type RM Length L Ch R = 1 ,1435.2,335.284,323.642,313.806
XS GIS Cut Line= 3
     1762591.859      265193.568     1762047.797      265244.073
     1761458.950      265303.252
#Sta/Elev= 30
       0 1165.96    54.4 1163.49    67.5 1161.60    86.1 1157.24    98.0 1153.86
   121.9 1145.92   221.6 1108.92   241.1 1102.93   300.7 1087.15   324.6 1082.27
   372.3 1070.83   443.8 1051.79   475.0 1043.89   503.4 1037.26   527.3 1030.41
   536.4 1028.25   539.2 1027.59   548.9 1027.25   551.4 1027.26   711.5 1032.31
   765.9 1037.17   787.4 1038.53   819.9 1038.78   861.4 1038.20   906.7 1040.72
   944.9 1041.47   980.7 1046.23  1040.4 1052.78  1076.2 1058.13  1138.2 1065.52
#Mann= 3 , 0 , 0
       0     0.1       0   536.4   0.045       0   551.4     0.1       0
Bank Sta=   536.4,   551.4
Exp/Cntr=0.3,0.1

Type RM Length L Ch R = 1 ,1111.5,366.991,364.023,358.431
XS GIS Cut Line= 3
     1762254.226      264728.491     1761837.428      265012.022
     1761365.628      265284.721
#Sta/Elev= 30
       0 1158.21     8.9 1156.12    40.0 1147.41    54.3 1143.08    97.4 1128.96
   140.5 1115.96   169.2 1108.00   256.7 1084.74   298.4 1074.06   325.1 1067.71
   370.2 1057.80   413.3 1049.38   427.6 1046.17   470.8 1035.51   496.6 1027.36
   499.5 1026.86   511.6 1026.51   513.0 1026.48   540.8 1027.51   626.2 1027.41
   661.0 1027.80   702.8 1028.74   746.5 1030.80   765.3 1032.83   828.8 1040.80
   892.6 1046.43   940.1 1051.18   963.8 1054.81  1011.2 1063.40  1049.0 1069.46
#Mann= 3 , 0 , 0
       0     0.1       0   496.6   0.045       0   511.6     0.1       0
Bank Sta=   496.6,   511.6
Exp/Cntr=0.3,0.1

Type RM Length L Ch R = 1 ,747.5,432.06,435.977,439.194
XS GIS Cut Line= 3
     1762080.869      264361.031     1761707.851      264669.129
     1761178.714      265156.622
#Sta/Elev= 30
       0 1079.25    87.6 1079.33   126.0 1077.45   141.4 1076.21   156.8 1074.12
   187.6 1068.35   247.8 1059.81   264.9 1057.87   283.5 1056.71   302.2 1054.63
   374.3 1042.17   450.2 1029.85   458.7 1028.81   505.8 1026.31   569.1 1025.70
   575.9 1025.48   584.1 1025.74   601.6 1026.64   625.3 1027.14   681.0 1026.90
   754.4 1027.36   878.9 1026.77   887.3 1027.40   891.3 1028.07   964.3 1042.62
  1012.7 1049.21  1125.7 1058.53  1173.0 1060.30  1189.2 1060.36  1203.3 1059.69
#Mann= 3 , 0 , 0
       0     0.1       0   569.1   0.045       0   584.1     0.1       0
Bank Sta=   569.1,   584.1
Exp/Cntr=0.3,0.1

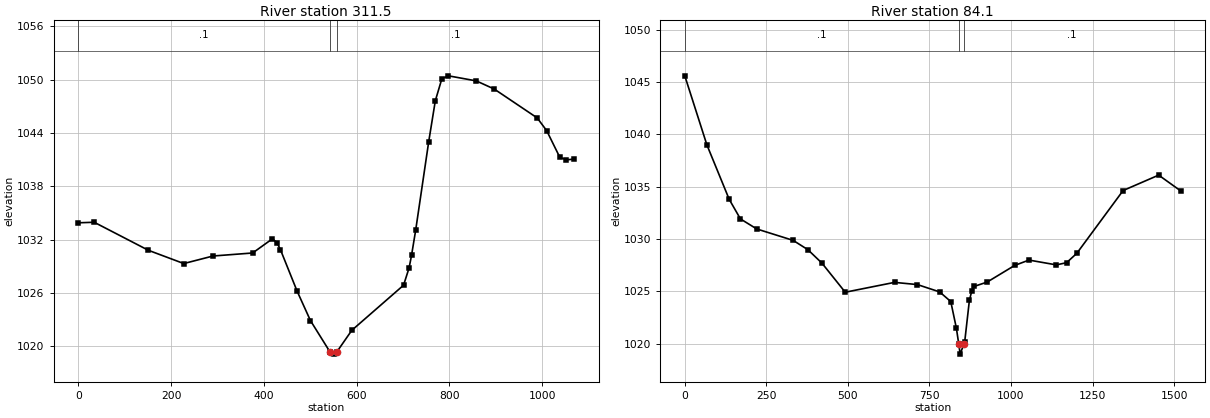
Type RM Length L Ch R = 1 ,311.5,224.873,227.473,226.83
XS GIS Cut Line= 3
     1761850.970      264254.495     1761396.757      264564.493
     1760960.382      264845.944
#Sta/Elev= 30
       0 1033.89    34.2 1033.95   151.2 1030.79   227.4 1029.30   290.5 1030.15
   375.9 1030.49   418.6 1032.09   428.6 1031.63   435.7 1030.88   471.7 1026.20
   500.5 1022.88   542.4 1019.37   551.4 1019.10   557.4 1019.35   589.7 1021.78
   701.3 1026.86   713.3 1028.82   718.5 1030.22   727.4 1033.04   755.6 1043.04
   769.8 1047.63   783.9 1050.11   798.0 1050.44   858.1 1049.87   896.9 1048.95
   989.5 1045.70  1009.9 1044.27  1038.2 1041.27  1052.3 1040.98  1069.2 1041.06
#Mann= 3 , 0 , 0
       0     0.1       0   542.4   0.045       0   557.4     0.1       0
Bank Sta=   542.4,   557.4
Exp/Cntr=0.3,0.1

Type RM Length L Ch R = 1 ,84.1,84.707,84.062,82.79
XS GIS Cut Line= 5
     1762141.469      264106.043     1761657.259      264192.892
     1761361.611      264394.671     1761126.674      264546.199
     1760869.873      264841.002
#Sta/Elev= 30
       0 1045.59    67.7 1039.00   136.1 1033.80   170.5 1031.93   220.6 1030.97
   332.2 1029.88   377.4 1028.99   420.4 1027.71   491.9 1024.93   642.9 1025.87
   713.0 1025.66   781.3 1024.96   815.4 1024.04   832.6 1021.50   840.1 1019.94
   844.2 1019.02   855.1 1019.94   858.1 1020.19   872.5 1024.15   880.0 1025.08
   886.6 1025.48   927.0 1025.90  1011.4 1027.49  1055.2 1028.00  1139.1 1027.54
  1170.5 1027.75  1202.0 1028.65  1343.8 1034.64  1452.8 1036.11  1520.1 1034.61
#Mann= 3 , 0 , 0
       0     0.1       0   840.1   0.045       0   855.1     0.1       0
Bank Sta=   840.1,   855.1
Exp/Cntr=0.3,0.1